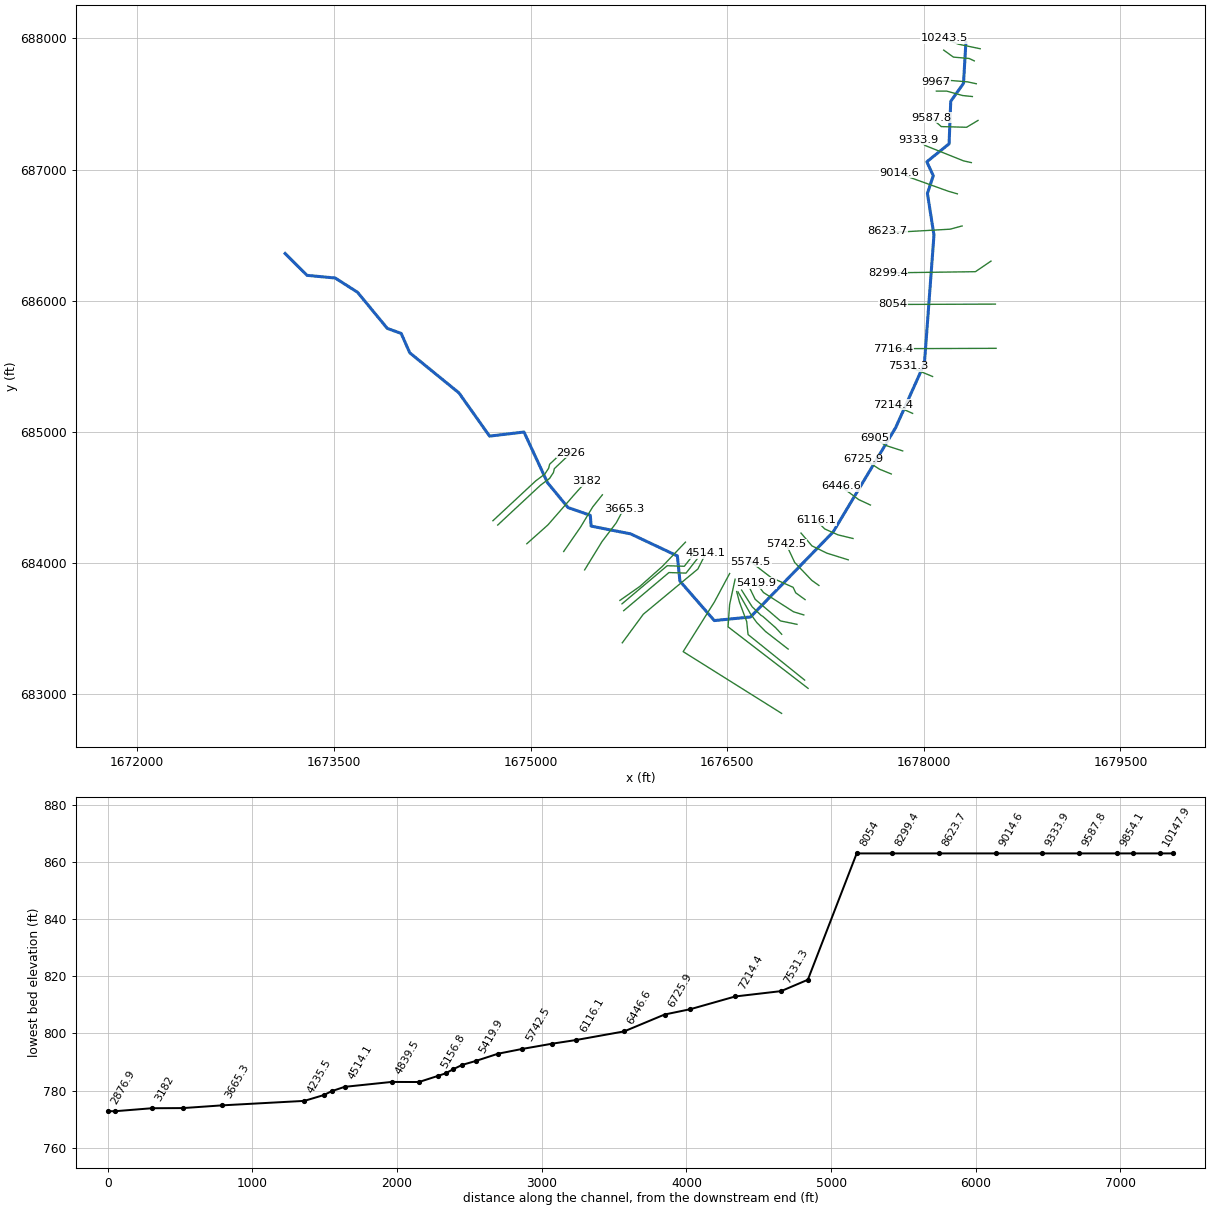
--- ALXNDRSRN.prj (project) ---

Proj Title=ALXNDRSRN
Current Plan=p01
Default Exp/Contr=0,0
English Units
Geom File=g01
Flow File=f01
Plan File=p01
BEGIN DESCRIPTION:
END DESCRIPTION:
DSS Export Rating Curves= 0
DSS Export Rating Curve Sorted= 0
DSS Export Volume Flow Curves= 0
DXF Filename=..\..\..\..\..\Engineering\Hydraulics\ALXNDRSRN\ALXNDRSRN.
DXF OffsetX= 0
DXF OffsetY= 0
DXF ScaleX= 0
DXF ScaleY= 0

--- ALXNDRSRN.p01 (plan) ---

Plan Title=Floodplain
Program Version=4.00
Geom File=g01
Flow File=f01
K Sum by GR=0
Std Step Tol=0.01
Critical Tol=0.01
Num of Std Step Trials=20
Max Error Tol=0.3
Flow Tol Ratio=0.001
Split Flow NTrial=30
Split Flow Tol=0.02
Split Flow Ratio=0.02
Log Output Level=0
Friction Slope Method=1
Unsteady Friction Slope Method=2
Unsteady Bridges Friction Slope Method=1
Global Log Level=0
CheckData=False
Run HTab=0
Run UNet=0
Run PostProcess=0
UNET Theta=0
UNET Theta Warmup=0
UNET ZTol=0
UNET ZSATol=0
UNET MxIter=0
UNET MaxInSteps=0
UNET DtIC=0
UNET DtMin=0
UNET MaxCRTS=0
UNET WFStab=0
UNET SFStab=0
UNET WFX=0
UNET SFX=0
UNET DSS MLevel=0
UNET DZMax Abort=0
UNET Convert EG Bridges=0
UNET Use Existing IB Tables=0
UNET Froude Limit=0
UNET Froude Power=0
Write IC File=0
Echo Input=False
Echo Output=False
Write Detailed=0

--- ALXNDRSRN.f01 (steady flow) ---

Flow Title=NFF Regression Equation
Program Version=4.10
Number of Profiles= 1
Profile Names=P100yr
River Rch & RM=ALXNDRSRN,Main            ,10243.5
859.8912
River Rch & RM=ALXNDRSRN,Main            ,8623.7
947.1375
River Rch & RM=ALXNDRSRN,Main            ,5419.9
1046.193
Boundary for River Rch & Prof#=ALXNDRSRN,Main            , 1
Up Type= 0
Dn Type= 3
Dn Slope=0.003
DSS Import GetInterval= 0
DSS Import GetPeak= 0
DSS Import FillOption= 0

--- ALXNDRSRN.g01 (geometry) ---

Geom Title=2003 WVU SAMB 3 Meter DEM
Program Version=4.10

River Reach=ALXNDRSRN       ,Main
Reach XY= 30
     1678320.892      687971.268     1678302.557      687657.348
     1678205.215      687520.081     1678192.597      687196.048
     1678022.923      687059.143     1678072.076      686952.708
     1678027.263      686817.824     1678077.263       686499.71
     1678004.347      685519.924     1677785.857      685032.684
     1677308.513      684235.809     1676677.935      683586.905
     1676401.743      683559.507     1676139.462      683860.425
     1676119.963      684052.666     1675763.816      684220.639
     1675462.316      684280.099      1675455.91      684362.359
     1675286.369      684421.417     1675129.859      684610.479
     1674950.128       684997.64     1674687.594      684966.477
     1674453.913      685296.208     1674078.757       685601.89
     1674013.418      685749.768     1673907.515      685787.962
     1673680.084      686064.004     1673510.033      686172.376
     1673295.276      686192.775     1673128.001      686359.143

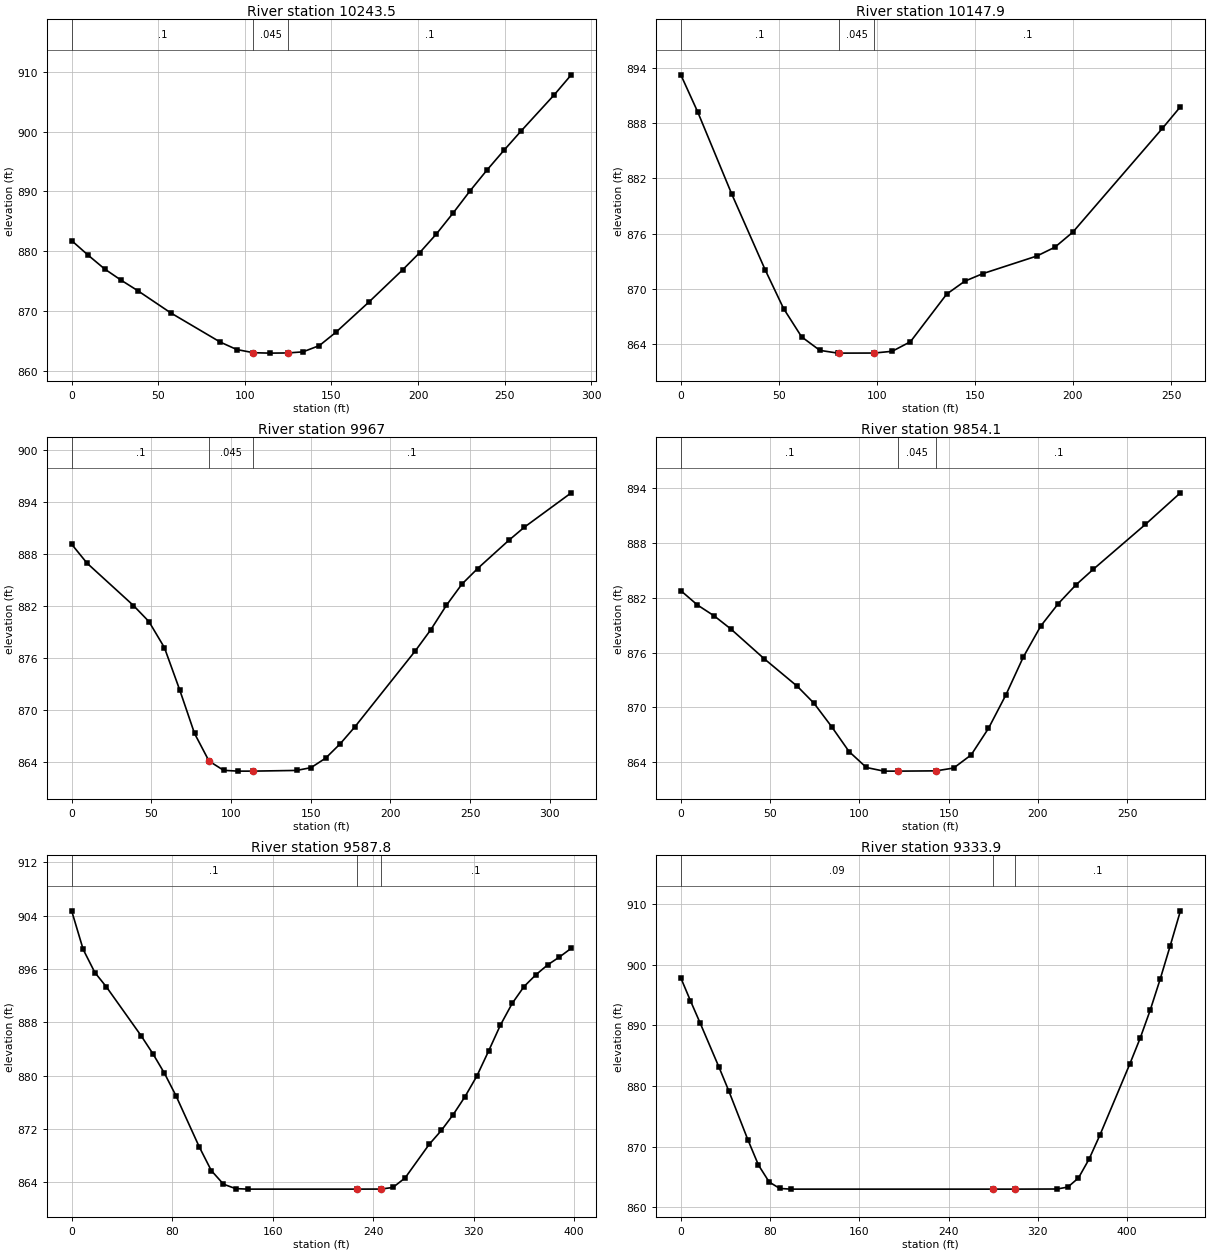
Type RM Length L Ch R = 1 ,10243.5 ,92.6,95.6,98
XS GIS Cut Line= 3
     1678430.084      687921.209     1678262.116      687956.365
     1678154.043      688000.636
#Sta/Elev= 25
       0  881.79     9.5  879.36    19.1  877.04    28.6  875.17    38.1  873.44
    57.2  869.72    85.8  864.84    95.3   863.6   104.9  863.07   114.4     863
   124.9  863.03   133.5  863.21     143  864.26   152.5  866.47   171.6  871.53
   191.1  876.92   200.8  879.74   210.5  882.88   220.3  886.43     230   890.1
   239.7  893.55   249.5  896.85   259.2  900.01   278.7  906.17   288.4  909.47
#Mann= 3 , 0 , 0
       0      .1       0   104.9    .045       0   124.9      .1       0
Bank Sta=104.9,124.9
XS Rating Curve= 0 ,0
Exp/Cntr=0.3,0.1

Type RM Length L Ch R = 1 ,10147.9 ,180.6,180.9,180.7
XS GIS Cut Line= 4
     1678384.511      687828.761     1678345.449       687846.99
     1678225.657      687857.407     1678151.439      687910.792
#Sta/Elev= 20
       0  893.26     8.6  889.23    25.9  880.33    43.1  872.02    52.4  867.85
    61.6  864.77    70.9   863.3    80.1     863    80.7     863    98.6  863.01
   107.8   863.2   117.1  864.24   135.6  869.42   144.8  870.82   154.1  871.65
   181.6  873.56   190.8  874.52   199.9  876.15   245.6  887.44   254.8  889.79
#Mann= 3 , 0 , 0
       0      .1       0    80.7    .045       0    98.6      .1       0
Bank Sta=80.7,98.6
XS Rating Curve= 0 ,0
Exp/Cntr=0.3,0.1

Type RM Length L Ch R = 1 ,9967    ,117.3,112.9,107.8
XS GIS Cut Line= 4
     1678400.136      687654.282      1678333.73      687668.605
     1678206.126      687679.021     1678088.939      687669.907
#Sta/Elev= 24
       0  889.17     9.7  886.98    38.8   882.1    48.5  880.25    58.2  877.25
    67.9  872.32    77.1  867.35    86.2  864.16    95.4  863.09   104.5     863
   113.7     863   141.1  863.08   150.2   863.4   159.4   864.5   168.5  866.15
   177.7   868.1   215.6  876.86   225.4  879.32   235.1  882.11   244.9  884.57
   254.7  886.36   274.3  889.62   284.1  891.14   313.5   895.1
#Mann= 3 , 0 , 0
       0      .1       0    86.2    .045       0   113.7      .1       0
Bank Sta=86.2,113.7
XS Rating Curve= 0 ,0
Exp/Cntr=0.3,0.1

Type RM Length L Ch R = 1 ,9854.1  ,260.9,266.3,271.7
XS GIS Cut Line= 4
     1678370.189      687556.626      1678295.97      687564.438
     1678173.574      687598.292     1678095.449      687598.292
#Sta/Elev= 24
       0  882.79     9.3  881.22    18.7  880.02      28  878.59    46.6  875.34
    65.3  872.29    74.6  870.44    84.4  867.89    94.2  865.15   103.9   863.4
   113.7     863   121.9     863     143  863.03   152.8  863.34   162.6  864.78
   172.3  867.69   182.1  871.38   191.8  875.51   201.6  878.92   211.4  881.37
   221.2  883.41   230.9  885.12   260.2  890.06   279.8  893.52
#Mann= 3 , 0 , 0
       0      .1       0   121.9    .045       0     143      .1       0
Bank Sta=121.9,143
XS Rating Curve= 0 ,0
Exp/Cntr=0.3,0.1

Type RM Length L Ch R = 1 ,9587.8  ,261.7,253.9,244.5
XS GIS Cut Line= 4
     1678413.157      687374.334     1678325.918      687322.251
     1678133.209      687327.459     1678055.084      687395.167
#Sta/Elev= 30
       0  904.75     9.2  898.95    18.5  895.49    27.7  893.33    55.4  885.99
    64.7  883.31    73.9  880.38    83.1     877   101.6  869.34   111.2  865.78
   120.9  863.74   130.5  863.08   140.2     863   226.9     863   246.2  863.01
   255.8  863.25   265.5  864.68   284.7  869.72   294.4  871.81   303.8  874.18
   313.2  876.87   322.6  879.95     332  883.72   341.4  887.61   350.8  890.87
   360.2  893.39   369.6  895.15     379  896.64   388.4  897.82   397.8  899.13
#Mann= 3 , 0 , 0
       0      .1       0   226.9    .045       0   246.2      .1       0
Bank Sta=226.9,246.2
XS Rating Curve= 0 ,0
Exp/Cntr=0.3,0.1

Type RM Length L Ch R = 1 ,9333.9  ,321.9,319.4,317.4
XS GIS Cut Line= 4
     1678362.376      687052.719     1678303.782       687065.74
     1678010.814      687182.928     1677954.824      687228.501
#Sta/Elev= 23
       0  897.82     8.6  894.06    17.2  890.43    34.3  883.06    42.9  879.23
      60  871.18    69.6  866.96    79.2  864.17    88.7  863.11    98.3     863
   279.9     863   299.1     863   337.3  863.02   346.9  863.34   356.4  864.84
     366  867.98   375.6   871.9   402.6  883.71   411.7  887.88   420.7   892.5
   429.7  897.65   438.7  903.16   447.8  908.88
#Mann= 3 , 0 , 0
       0     .09       0   279.9    .045       0   299.1      .1       0
Bank Sta=279.9,299.1
XS Rating Curve= 0 ,0
Exp/Cntr=0.3,0.1

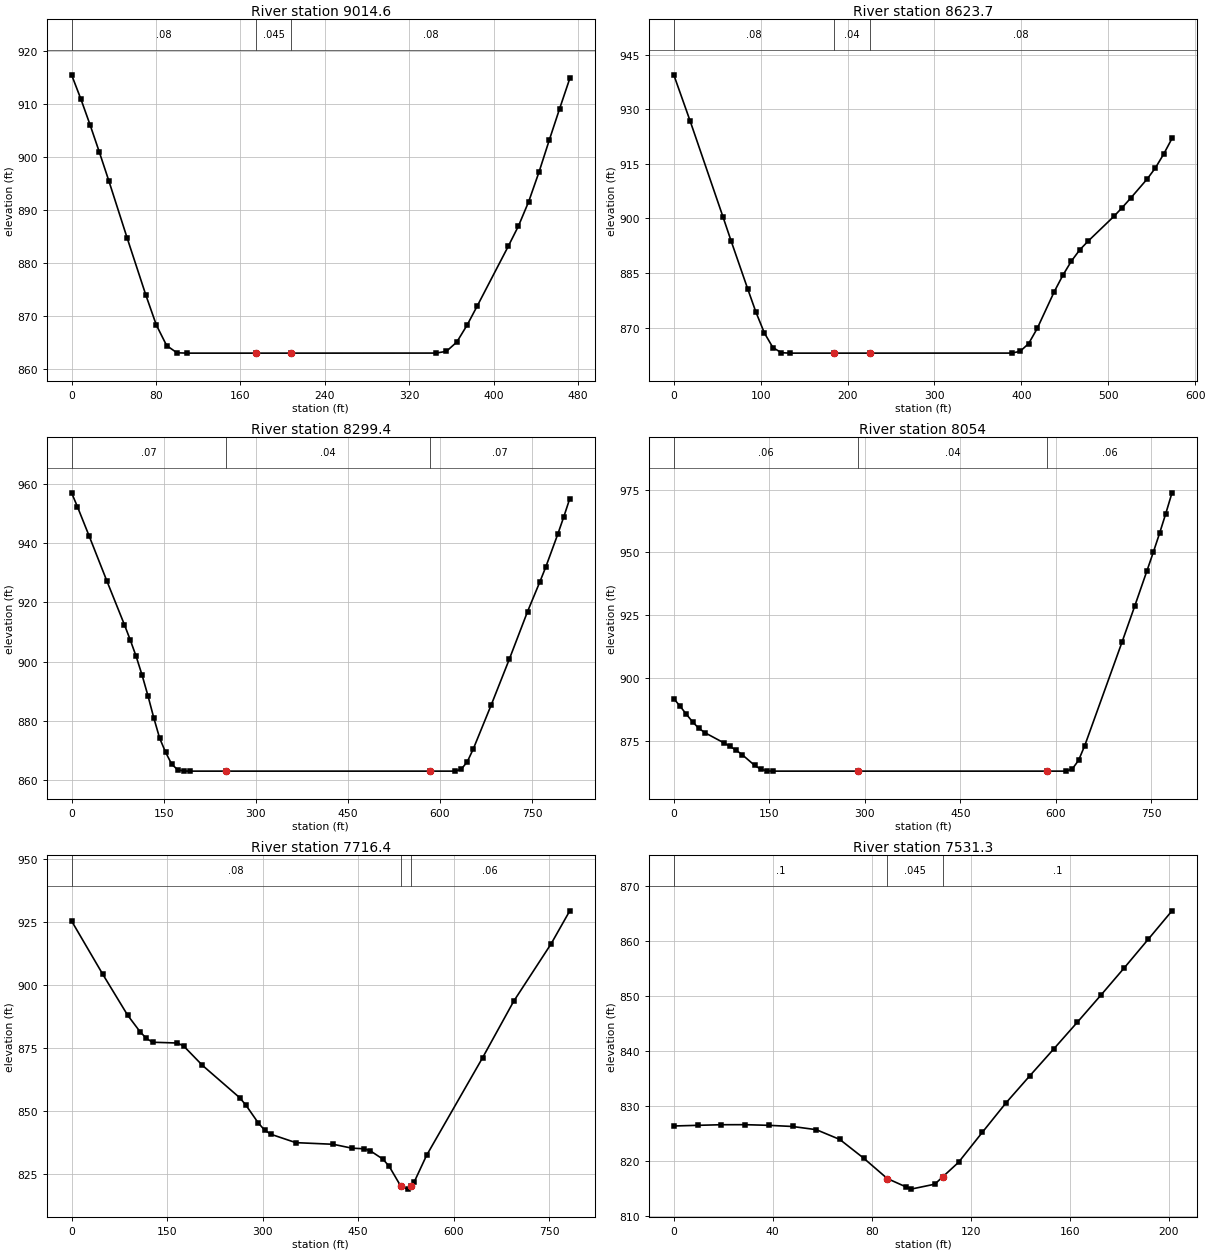
Type RM Length L Ch R = 1 ,9014.6  ,375.1,390.9,395.4
XS GIS Cut Line= 4
     1678255.605      686814.438     1678187.897      686833.969
     1677901.439      686936.834     1677812.897      686977.199
#Sta/Elev= 25
       0  915.46     8.8   910.9    17.6  905.99    26.4  900.84    35.2  895.54
    52.8  884.62    70.5  873.87    80.3  868.31    90.1  864.42    99.9  863.06
   109.7     863     175     863   207.9     863   345.4  863.01   355.2  863.34
     365  865.08   374.8  868.28   384.6  871.96   413.8  883.14   423.5  886.98
   433.2  891.58     443  897.17   452.7  903.18   462.4  909.04   472.1  914.77
#Mann= 3 , 0 , 0
       0     .08       0     175    .045       0   207.9     .08       0
Bank Sta=175,207.9
XS Rating Curve= 0 ,0
Exp/Cntr=0.3,0.1

Type RM Length L Ch R = 1 ,8623.7  ,325.3,324.3,323.3
XS GIS Cut Line= 4
     1678292.064      686569.646     1678200.918      686544.907
     1677789.459      686521.469     1677723.053      686529.282
#Sta/Elev= 28
       0  939.43    18.9  926.69    56.7  900.37    66.1  893.72      85   880.7
    94.4  874.35   104.3  868.52   114.1  864.52   123.9  863.11   133.7     863
     184     863   225.8     863   388.8  863.01   398.6  863.49   408.4  865.62
   418.3  869.78   437.9  879.88   447.7  884.34   457.5  888.24   467.3  891.38
   477.1  893.81   506.6  900.57   516.1  902.97   525.7  905.53   544.8  910.81
   554.3  913.86   563.9  917.69   573.4  921.95
#Mann= 3 , 0 , 0
       0     .08       0     184     .04       0   225.8     .08       0
Bank Sta=184,225.8
XS Rating Curve= 0 ,0
Exp/Cntr=0.3,0.1

Type RM Length L Ch R = 1 ,8299.4  ,245.6,245.4,245.1
XS GIS Cut Line= 3
     1678512.116      686301.417     1678393.626      686220.688
     1677725.657      686211.574
#Sta/Elev= 30
       0  956.93     9.6  952.21    28.7  942.31    57.4  927.22      86  912.45
    95.6  907.26   105.1  901.76   114.7  895.49   124.3  888.51   133.8  881.04
   143.4  874.14   153.2  869.34     163  865.36   172.8  863.46   182.7  863.03
   192.5     863     252     863     583     863   624.8     863   634.6  863.64
   644.4  866.13   654.2  870.47   683.7  885.47   713.2  900.93   742.6  916.85
   762.3   926.7   772.1  931.78   791.8  942.94   801.6  948.81   811.4  954.99
#Mann= 3 , 0 , 0
       0     .07       0     252     .04       0     583     .07       0
Bank Sta=252,583
XS Rating Curve= 0 ,0
Exp/Cntr=0.3,0.1

Type RM Length L Ch R = 1 ,8054    ,337.4,337.6,337.4
XS GIS Cut Line= 2
      1678545.97      685973.292     1677763.418      685970.688
#Sta/Elev= 27
       0  891.83     9.8  888.85    19.6  885.68    29.4  882.63    39.1  880.08
    48.9  878.28    78.3  874.29      88  872.89    97.8  871.34   107.6  869.51
   127.2  865.24     137   863.7   146.7  863.08   156.5     863     290     863
     586     863   616.3     863     626  863.87   635.8  867.27   645.6  873.18
   704.3  914.46   723.9  928.52   743.4  942.78   753.2  950.03     763  957.52
   772.8  965.41   782.6  973.69
#Mann= 3 , 0 , 0
       0     .06       0     290     .04       0     586     .06       0
Bank Sta=290,586
XS Rating Curve= 0 ,0
Exp/Cntr=0.3,0.1

Type RM Length L Ch R = 1 ,7716.4  ,193.6,185.1,175.8
XS GIS Cut Line= 2
     1678551.178      685636.053     1677768.626      685633.449
#Sta/Elev= 30
       0  925.34    48.9   904.2      88  887.93   107.6  881.32   117.4  878.72
   127.2  877.16   166.3  876.85   176.1  875.65   205.4  868.01   264.1  855.12
   273.9  852.15   293.5  845.02   303.2  842.27     313  840.61   352.2  837.27
   410.8  836.62   440.2  835.08   459.8  834.82   469.5  833.98   489.1  830.71
   498.9  827.86   517.4  819.85   528.2   818.8   532.4  819.97     538  821.52
   557.6  832.19   645.6  870.99   694.5  893.44   753.2  916.23   782.6  929.37
#Mann= 3 , 0 , 0
       0     .08       0   517.4    .045       0   532.4     .06       0
Bank Sta=517.4,532.4
XS Rating Curve= 0 ,0
Exp/Cntr=0.3,0.1

Type RM Length L Ch R = 1 ,7531.3  ,317.4,317,316.4
XS GIS Cut Line= 2
     1678066.803      685421.209     1677880.605      685498.032
#Sta/Elev= 24
       0  826.32     9.6  826.44    19.2  826.55    28.8  826.56    38.4  826.44
      48  826.23    57.6  825.65    67.1  823.87    76.7  820.48    86.3  816.75
    93.8  815.24    95.9  814.82   105.5  815.72   108.8  817.09   115.1   819.7
   124.7  825.15   134.3  830.53   143.9  835.45   153.5   840.3   163.1   845.2
   172.6  850.12   182.2  855.17   191.8  860.33   201.4  865.51
#Mann= 3 , 0 , 0
       0      .1       0    86.3    .045       0   108.8      .1       0
Bank Sta=86.3,108.8
XS Rating Curve= 0 ,0
Exp/Cntr=0.3,0.1

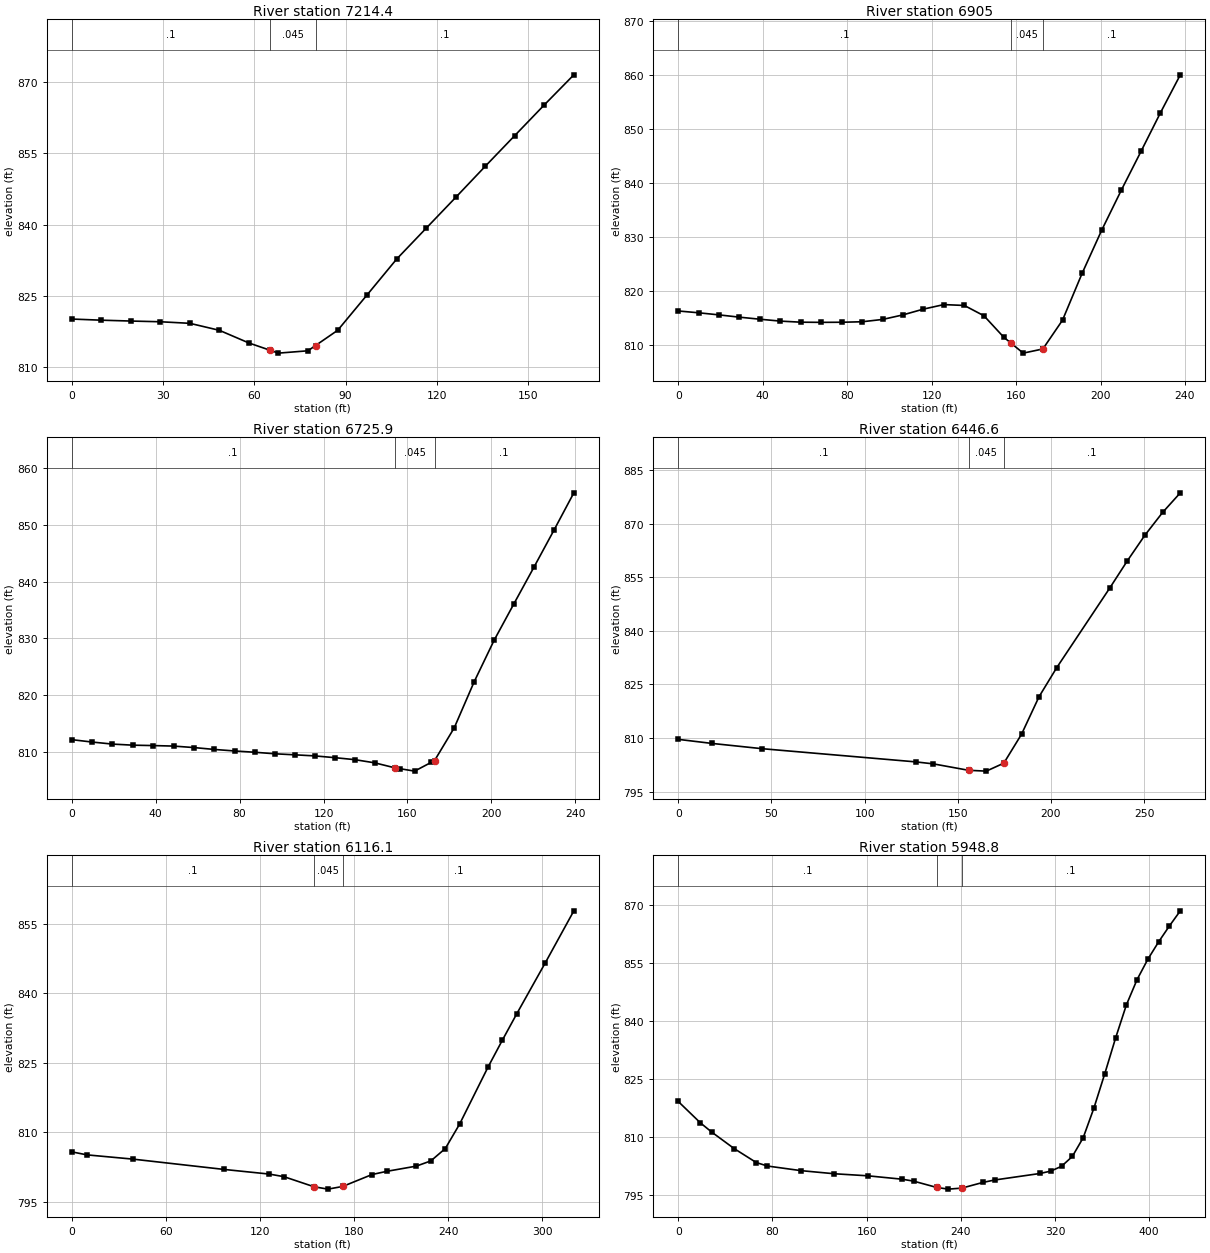
Type RM Length L Ch R = 1 ,7214.4  ,312.3,309.3,306.2
XS GIS Cut Line= 2
     1677914.459      685139.959     1677763.418      685206.365
#Sta/Elev= 20
       0  820.12     9.7  819.88    19.4   819.7    29.1  819.55    38.8  819.22
    48.5  817.75    58.2  815.09    65.1  813.57    67.9  812.95    77.6  813.44
    80.1  814.54    87.4  817.76    97.1  825.24   106.8  832.76   116.5  839.25
   126.2  845.73   135.9  852.27   145.6  858.73   155.3  865.18     165   871.5
#Mann= 3 , 0 , 0
       0      .1       0    65.1    .045       0    80.1      .1       0
Bank Sta=65.1,80.1
XS Rating Curve= 0 ,0
Exp/Cntr=0.3,0.1

Type RM Length L Ch R = 1 ,6905    ,179.5,179.1,178.5
XS GIS Cut Line= 3
     1677838.939      684853.501     1677710.032      684895.167
     1677622.793      684948.553
#Sta/Elev= 28
       0  816.32     9.7  815.98    19.4  815.59      29  815.17    38.7  814.79
    48.4  814.44    58.1  814.24    67.7  814.21    77.4  814.23    87.1  814.32
    96.8  814.75   106.4  815.59   116.1  816.66   125.8   817.5   135.5  817.34
   144.8  815.43   154.1  811.49   157.8   810.3   163.4  808.51   172.7  809.28
   172.8  809.34     182  814.61   191.3   823.3   200.6  831.31   209.9  838.73
   219.2  845.89   228.4  853.04   237.8  860.06
#Mann= 3 , 0 , 0
       0      .1       0   157.8    .045       0   172.8      .1       0
Bank Sta=157.8,172.8
XS Rating Curve= 0 ,0
Exp/Cntr=0.3,0.1

Type RM Length L Ch R = 1 ,6725.9  ,280.2,279.3,277.2
XS GIS Cut Line= 3
     1677751.699      684677.719     1677661.855      684714.178
     1677542.064      684791.001
#Sta/Elev= 28
       0  812.17     9.7  811.75    19.4  811.39    29.1   811.2    38.8  811.13
    48.5  811.04    58.2  810.78    67.9  810.45    77.6  810.18    87.3  809.95
      97  809.68   106.4   809.5   115.9  809.31   125.4     809   134.9  808.65
   144.4  808.09   153.9  807.22   156.4  807.06   163.4  806.63   171.4  808.19
   172.9  808.48   182.3  814.26   191.8  822.37   201.3  829.67   210.8  836.14
   220.3  842.55   229.8  849.04   239.3  855.63
#Mann= 3 , 0 , 0
       0      .1       0   153.9    .045       0   172.9      .1       0
Bank Sta=153.9,172.9
XS Rating Curve= 0 ,0
Exp/Cntr=0.3,0.1

Type RM Length L Ch R = 1 ,6446.6  ,325.2,330.5,335.6
XS GIS Cut Line= 3
     1677592.845       684440.74     1677503.001      684482.407
     1677366.282      684583.969
#Sta/Elev= 16
       0  809.62      18  808.49      45  807.01   127.4  803.32   136.9  802.76
   155.8  800.96   165.3  800.73   174.7  802.96   184.2  811.05   193.6  821.56
   203.1   829.7   231.5  851.94     241  859.61   250.4  866.76   259.9  873.13
   269.4  878.62
#Mann= 3 , 0 , 0
       0      .1       0   155.8    .045       0   174.7      .1       0
Bank Sta=155.8,174.7
XS Rating Curve= 0 ,0
Exp/Cntr=0.3,0.1

Type RM Length L Ch R = 1 ,6116.1  ,165.6,167.3,164.4
XS GIS Cut Line= 4
     1677460.032      684185.532     1677346.751      684212.876
     1677243.886      684258.449     1677180.084      684323.553
#Sta/Elev= 20
       0  805.77     9.7  805.12    38.8  804.21    97.1  801.98   125.9  800.98
   135.3  800.42   154.5  798.24   163.4  797.73   172.8  798.31   191.5  800.88
   200.9  801.57   219.7  802.69     229  803.82   238.2  806.48   247.3  811.73
   265.5  824.08   274.6  829.86   283.7   835.5     302  846.56   320.2  857.77
#Mann= 3 , 0 , 0
       0      .1       0   154.5    .045       0   172.8      .1       0
Bank Sta=154.5,172.8
XS Rating Curve= 0 ,0
Exp/Cntr=0.3,0.1

Type RM Length L Ch R = 1 ,5948.8  ,214.7,206.3,198.2
XS GIS Cut Line= 4
     1677423.574      684022.771     1677260.814      684073.553
      1677146.23      684129.542     1677062.897      684227.199
#Sta/Elev= 30
       0  819.13    18.9  813.57    28.4  811.21    47.4  806.95    66.3  803.31
    75.8  802.41   104.2  801.22   132.6  800.41     161  799.88   190.1     799
   199.9   798.5   219.6  796.86   229.4  796.43   240.8  796.69   258.8  798.17
   268.6  798.79   307.2  800.48   316.4   801.1   325.5  802.34   334.7  804.89
   343.9  809.73     353   817.4   362.2  826.27   371.4  835.53   380.6  844.14
   389.7  850.71   398.9     856   408.1  860.52   417.2  864.61   426.4   868.5
#Mann= 3 , 0 , 0
       0      .1       0   219.6    .045       0   240.8      .1       0
Bank Sta=219.6,240.8
XS Rating Curve= 0 ,0
Exp/Cntr=0.3,0.1

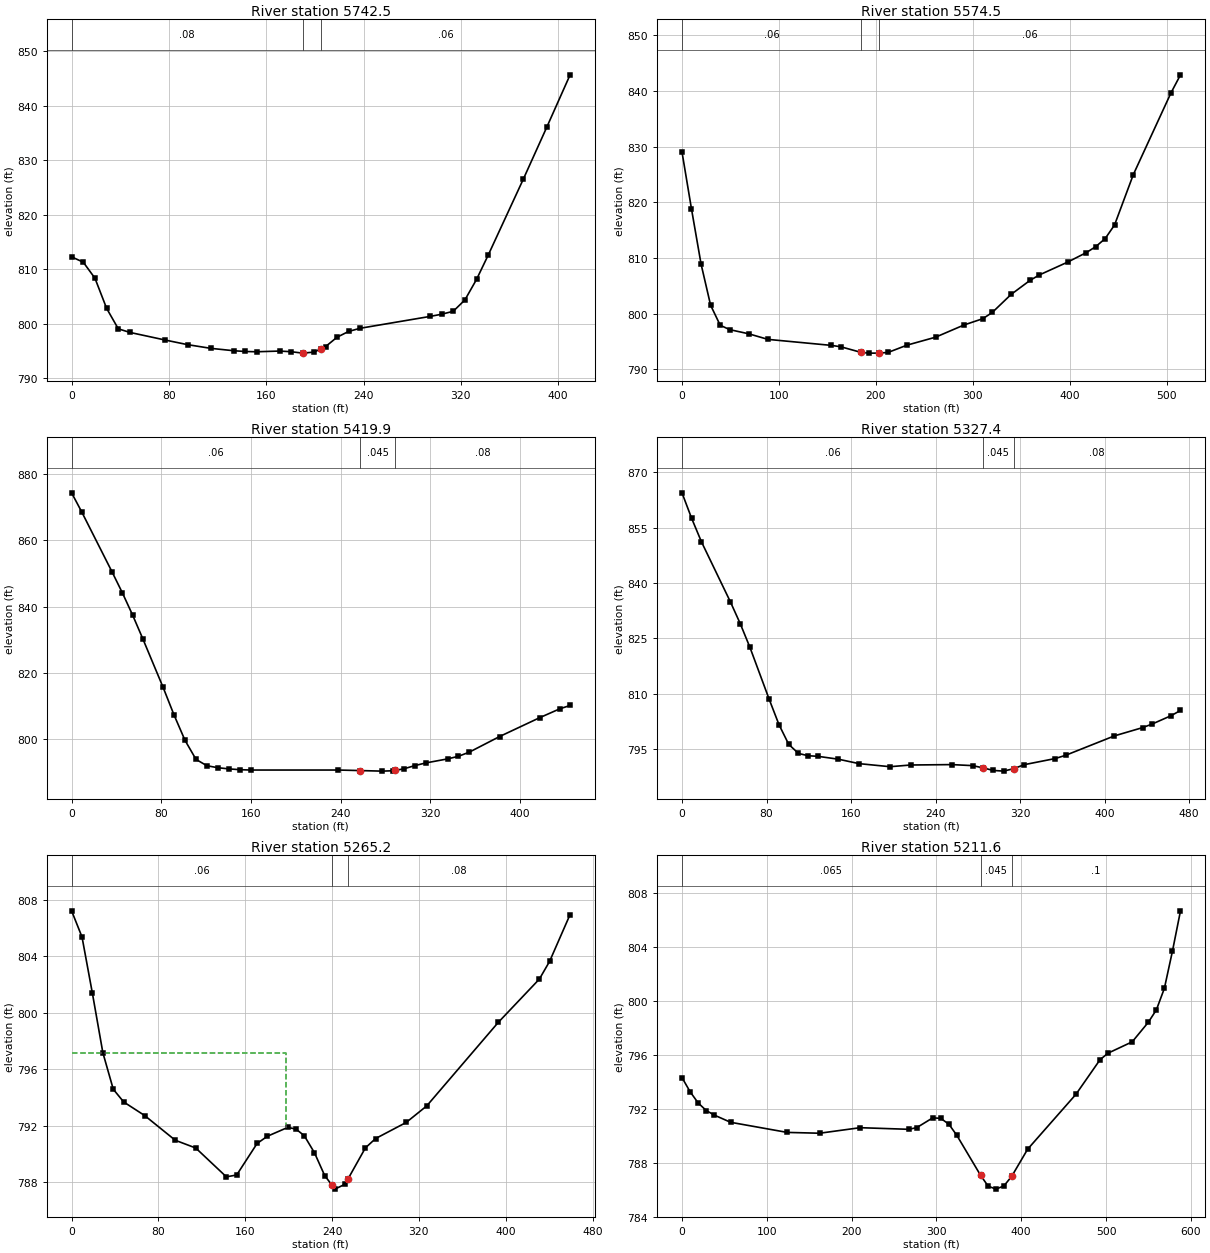
Type RM Length L Ch R = 1 ,5742.5  ,158.1,168,177
XS GIS Cut Line= 4
     1677199.616      683827.459     1677144.928      683866.521
      1677014.72       684003.24     1676949.616      684142.563
#Sta/Elev= 30
       0  812.28     9.6   811.3    19.2  808.36    28.8  802.82    38.4  799.06
      48   798.4    76.6  797.02    95.5  796.15   114.4  795.48   133.3  795.04
   142.7   794.9   152.2  794.85     171  794.98   180.5  794.86   189.9   794.6
   199.4  794.79     205  795.39   208.8   795.8   218.2  797.52   227.7  798.58
   237.1  799.16   294.4  801.33   304.1  801.74   313.7  802.28   323.3  804.36
   332.9  808.14   342.5  812.61   371.4  826.58   390.6  836.08   409.8  845.71
#Mann= 3 , 0 , 0
       0     .08       0   189.9    .045       0     205     .06       0
Bank Sta=189.9,205
XS Rating Curve= 0 ,0
Exp/Cntr=0.3,0.1

Type RM Length L Ch R = 1 ,5574.5  ,157.4,154.5,151.2
XS GIS Cut Line= 5
     1677094.147      683719.386     1677022.532      683771.469
     1677003.001      683813.136      1676833.73      683888.657
     1676680.084      684007.146
#Sta/Elev= 30
       0  829.07     9.8  818.82    19.7   808.9    29.5  801.53    39.4  797.93
    49.2  797.14    68.9  796.39    88.6  795.39   154.1  794.31   163.8  794.06
   184.7  793.05   193.1  792.92   202.9  792.92   212.6  793.05   232.1  794.36
   261.4  795.78   290.7  797.97   310.2  799.11   319.9  800.22   339.3  803.46
   358.7  805.97   368.4  806.96   397.5  809.26   416.9  810.98   426.6  812.05
   436.3  813.49     446  815.94   465.4  825.01   504.2  839.68     514  842.92
#Mann= 3 , 0 , 0
       0     .06       0   184.7    .045       0   202.9     .06       0
Bank Sta=184.7,202.9
XS Rating Curve= 0 ,0
Exp/Cntr=0.3,0.1

Type RM Length L Ch R = 1 ,5419.9  ,95.7,92.5,89
XS GIS Cut Line= 4
     1677084.439      683602.488     1677006.314      683626.359
     1676776.279      683773.929     1676722.026      683845.543
#Sta/Elev= 30
       0  874.34     9.1  868.54    36.3  850.35    45.4   844.1    54.5  837.42
    63.5  830.34    81.7  815.61    91.4  807.32   101.2  799.66     111  793.92
   120.7     792   130.5   791.4   140.2  791.05     150  790.81   159.8   790.7
   237.9   790.7   257.4  790.54   276.9  790.37   286.7  790.48   288.6  790.59
   296.4  791.06   306.2  792.03     316  792.84   335.5  794.06   345.2  794.85
     355  796.12   381.9  800.81   417.9  806.53   435.8   809.2   444.8  810.18
#Mann= 3 , 0 , 0
       0     .06       0   257.4    .045       0   288.6     .08       0
Bank Sta=257.4,288.6
XS Rating Curve= 0 ,0
Exp/Cntr=0.3,0.1

Type RM Length L Ch R = 1 ,5327.4  ,63.4,62.3,60.7
XS GIS Cut Line= 4
     1677032.356      683530.873     1676906.488      683556.915
     1676713.345      683721.846     1676674.283      683802.141
#Sta/Elev= 30
       0  864.47     9.2  857.51    18.4   851.2    45.9  834.86    55.1  829.02
    64.3  822.58    82.6  808.44    91.8  801.62     101  796.29   110.2  793.82
   119.4  793.19   128.5  793.04   148.1  792.25   167.6  791.05   196.9  790.22
   216.4  790.68   255.5  790.79   275.1  790.51   284.8  789.91   294.6  789.21
   304.4  789.02   314.1   789.7   323.9  790.77   353.2  792.43     363   793.3
   409.3  798.58   436.1  800.83     445  801.79   462.9  804.05   471.8  805.47
#Mann= 3 , 0 , 0
       0     .06       0   284.8    .045       0   314.1     .08       0
Bank Sta=284.8,314.1
XS Rating Curve= 0 ,0
Exp/Cntr=0.3,0.1

Type RM Length L Ch R = 1 ,5265.2  ,57.7,53.5,49.3
XS GIS Cut Line= 6
     1676915.761      683455.063     1676870.189      683504.542
      1676771.23      683591.782     1676758.209      683599.594
     1676690.501      683664.699     1676609.772      683792.303
#Sta/Elev= 30
       0  807.21     9.6  805.36    19.2  801.36    28.8  797.17    38.4  794.58
      48  793.68    67.3  792.72    95.5  790.97   114.4  790.42   142.6  788.38
   152.1  788.51   170.9  790.74   180.3  791.25   199.2  791.88   206.8  791.76
   214.4  791.29   223.8  790.08   233.2  788.47   239.9  787.79   242.6  787.51
     252  787.86   254.9  788.26   270.7  790.43   280.1  791.09   308.3  792.23
   327.2   793.4   393.2  799.32     431  802.38   440.4  803.63   459.3  806.95
#Mann= 3 , 0 , 0
       0     .06       0   239.9    .045       0   254.9     .08       0
#XS Ineff= 2 , 0
          197.96  797.15
Permanent Ineff=
       F       F
Bank Sta=239.9,254.9
XS Rating Curve= 0 ,0
Exp/Cntr=0.3,0.1

Type RM Length L Ch R = 1 ,5211.6  ,60.7,54.8,48.7
XS GIS Cut Line= 5
     1676965.081      683342.071     1676791.682      683476.827
     1676725.223      683544.907     1676676.612      683612.615
     1676582.862      683777.546
#Sta/Elev= 30
       0   794.3     9.6  793.25    19.1  792.42    28.6  791.86    38.2  791.52
    57.3  790.99   124.1  790.24   162.3  790.18   210.1  790.59   267.2  790.47
   276.7  790.59   295.7  791.32   305.2  791.28   314.8  790.84     324  790.03
     352 787.072     361  786.26   370.3  786.04   379.6  786.28   388.8  786.99
   407.6     789   464.5  793.06     493  795.63   502.4  796.11   530.9  796.95
   549.9   798.4   559.4  799.32   568.8  800.91   578.3  803.66   587.8  806.65
#Mann= 3 , 0 , 0
       0    .065       0     352    .045       0   388.8      .1       0
Bank Sta=352,388.8
XS Rating Curve= 0 ,0
Exp/Cntr=0.3,0.1

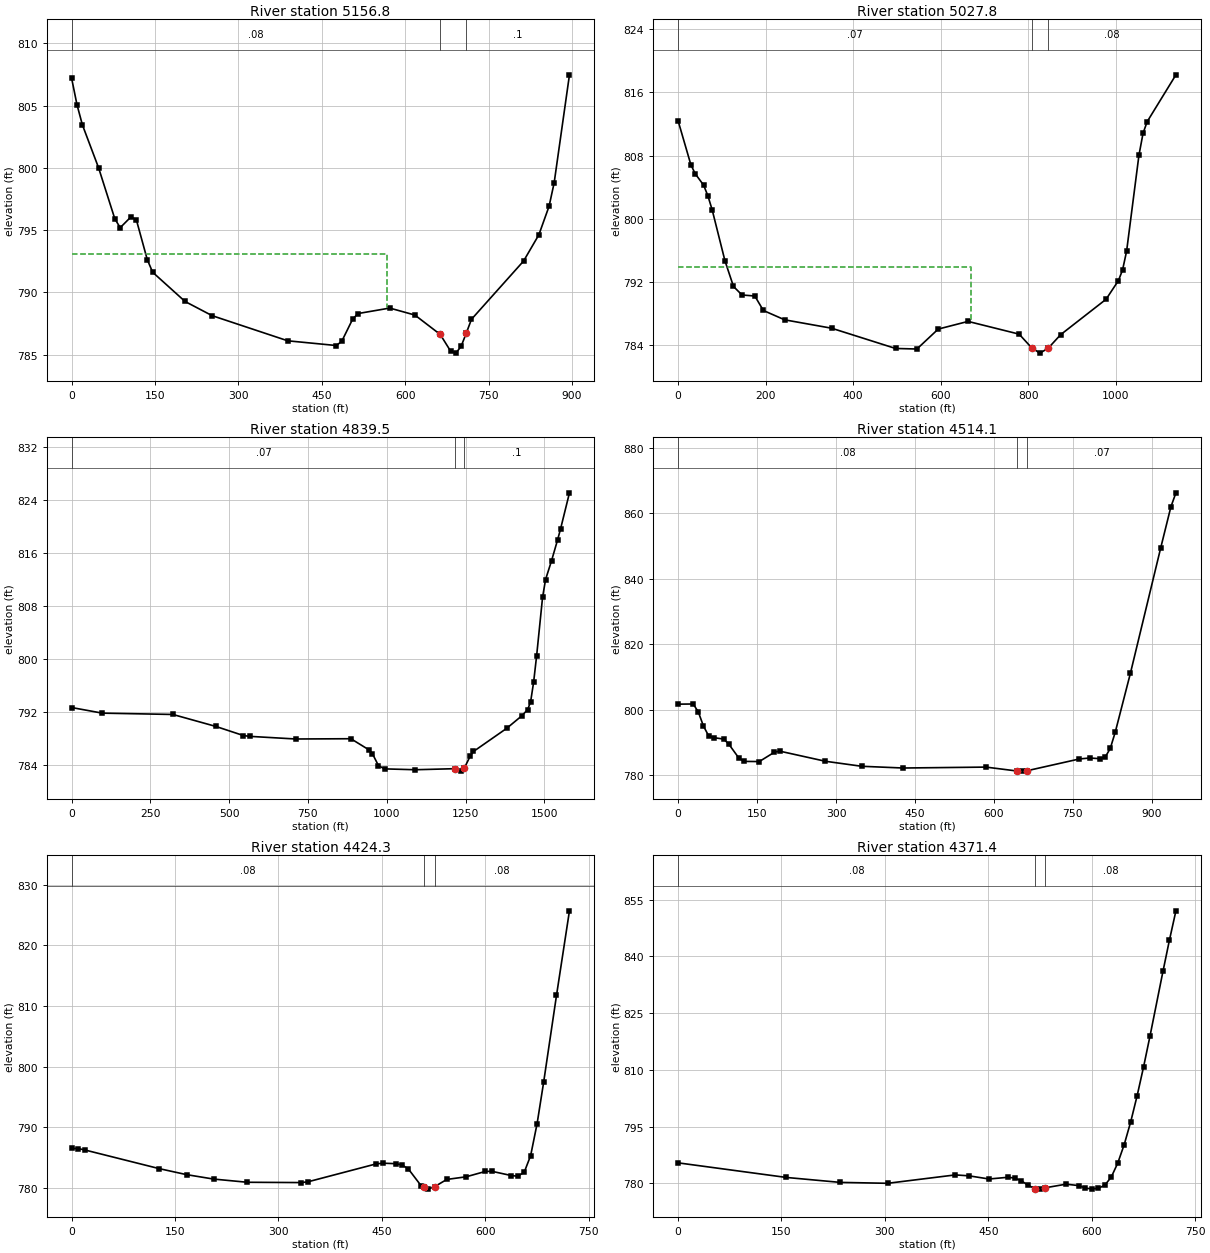
Type RM Length L Ch R = 1 ,5156.8  ,137.8,129,118.4
XS GIS Cut Line= 5
      1677090.95      683105.526     1676659.251      683452.893
     1676648.834      683551.851     1676593.279      683701.157
     1676572.445      683781.018
#Sta/Elev= 30
       0  807.23     9.7  805.09    19.4  803.47    48.6  800.01    77.8  795.91
    87.5   795.2   106.9  796.07   116.6  795.82   136.1  792.64   145.8  791.62
   204.1  789.27   252.8  788.13   388.8  786.11   476.3  785.73     486  786.08
   505.5  787.85   515.2   788.3   572.2  788.74   617.4  788.18     663  786.62
   681.7  785.28   691.1  785.12   700.5  785.66   709.8  786.72   719.2  787.84
   812.9  792.52   840.4  794.63   858.8  796.93   867.9  798.81   895.4  807.48
#Mann= 3 , 0 , 0
       0     .08       0     663    .045       0   709.8      .1       0
#XS Ineff= 2 , 0
          567.76  793.07
Permanent Ineff=
       F       F
Bank Sta=663,709.8
XS Rating Curve= 0 ,0
Exp/Cntr=0.3,0.1

Type RM Length L Ch R = 1 ,5027.8  ,199.1,188.4,176
XS GIS Cut Line= 4
     1677116.991      683042.592     1676506.473      683511.921
     1676518.626       683682.06     1676560.293      683874.768
#Sta/Elev= 30
       0  812.42    29.2  806.86      39  805.72    58.5  804.25    68.2  802.91
      78  801.14   107.2   794.7   126.7  791.45   146.2  790.37   175.5  790.24
     195  788.41   243.7  787.23   350.9  786.17   497.1  783.61   545.9  783.54
   594.6  786.06   662.8  787.03   779.5  785.42     808   783.7   826.9  783.02
   845.9  783.64   874.3  785.35   978.2  789.83  1006.4  792.19  1015.8  793.52
  1025.1  795.91  1053.3  808.04  1062.7  810.82  1072.1  812.28  1137.8   818.2
#Mann= 3 , 0 , 0
       0     .07       0     808    .045       0   845.9     .08       0
#XS Ineff= 2 , 0
          669.62  793.93
Permanent Ineff=
       F       F
Bank Sta=808,845.9
XS Rating Curve= 0 ,0
Exp/Cntr=0.3,0.1

Type RM Length L Ch R = 1 ,4839.5  ,333.7,325.4,316.7
XS GIS Cut Line= 4
     1676915.168       682851.62       1676164.3       683322.54
     1676402.307      683701.157     1676518.626      683918.171
#Sta/Elev= 30
       0  792.67    97.4  791.82   321.4  791.62   457.8  789.81   545.4  788.43
   564.9  788.31     711  787.91   886.3  787.95   944.6  786.24   954.4  785.71
   973.8  783.88   993.3  783.39  1090.5  783.26  1216.9  783.42  1236.3  783.05
    1246  783.48  1265.5  785.39  1275.2  786.02  1380.9  789.53  1428.2   791.4
  1447.2  792.36  1456.6  793.55  1466.1  796.51  1475.6  800.48  1494.5  809.35
    1504  812.03  1522.9  814.86  1541.9  817.99  1551.4  819.65  1579.8  825.14
#Mann= 3 , 0 , 0
       0     .07       0  1216.9    .045       0    1246      .1       0
Bank Sta=1216.9,1246
XS Rating Curve= 0 ,0
Exp/Cntr=0.3,0.1

Type RM Length L Ch R = 1 ,4514.1  ,103.6,89.8,70
XS GIS Cut Line= 4
      1675699.89      683389.814     1675859.772      683607.407
     1676276.439      683952.893     1676337.202      684072.685
#Sta/Elev= 30
       0  801.78    28.9  801.83    38.6  799.37    48.2  795.12    57.9  792.18
    67.5  791.56    86.8  791.12    96.4  789.58   115.7  785.28   125.4   784.3
   154.3  784.25   183.2  787.12   192.9  787.44   279.9  784.34   348.8  782.81
   427.5  782.28   584.9  782.56     644  781.36   653.8  781.33   663.1  781.46
   762.1  785.04   781.8  785.34   801.4  785.13   811.3  785.63   820.9  788.25
   830.5  793.31   859.3  811.31   916.8  849.57     936  862.01   945.6  866.31
#Mann= 3 , 0 , 0
       0     .08       0     644    .045       0   663.1     .07       0
Bank Sta=644,663.1
XS Rating Curve= 0 ,0
Exp/Cntr=0.3,0.1

Type RM Length L Ch R = 1 ,4424.3  ,53.1,53,54.4
XS GIS Cut Line= 4
     1675710.741       683635.04     1676055.793      683925.839
     1676186.002      683921.498     1676272.807      684032.175
#Sta/Elev= 30
       0  786.52     9.8   786.5    19.6  786.26   127.5  783.18   166.8   782.2
     206  781.47     255  780.94   333.5  780.89   343.3  781.03   441.4  783.96
   451.2  784.09   469.9  784.01   479.2  783.81   488.5  783.14   507.1  780.36
   511.7  780.09   516.4  779.81   526.7  780.22   544.3  781.41   572.2  781.84
   600.3  782.73   609.7  782.75   637.8  782.05   647.2  781.94   656.6   782.6
   665.9  785.34   675.3  790.63   684.7   797.4   703.4  811.76   722.2  825.71
#Mann= 3 , 0 , 0
       0     .08       0   511.7    .045       0   526.7     .08       0
Bank Sta=511.7,526.7
XS Rating Curve= 0 ,0
Exp/Cntr=0.3,0.1

Type RM Length L Ch R = 1 ,4371.4  ,140.1,135.8,147.8
XS GIS Cut Line= 4
      1675697.72      683687.123     1676042.772      683977.922
     1676172.981      683973.582     1676259.786      684084.259
#Sta/Elev= 30
       0  785.42     157  781.56   235.4  780.25   304.1  780.01   402.2  782.23
   421.8  781.99   451.2  781.15   479.2  781.61   488.5  781.38   497.8  780.71
   507.1  779.55   517.8   778.6   525.7  778.47   532.8  778.83   562.9  779.78
   581.5   779.4   590.9  778.72   600.3  778.54   609.7  778.68     619  779.51
   628.4  781.65   637.8  785.35   647.2  790.25   656.6  796.26   665.9  803.14
   675.3  810.82   684.7  819.04   703.4  836.05   712.8  844.33   722.2  852.06
#Mann= 3 , 0 , 0
       0     .08       0   517.8    .045       0   532.8     .08       0
Bank Sta=517.8,532.8
XS Rating Curve= 0 ,0
Exp/Cntr=0.3,0.1

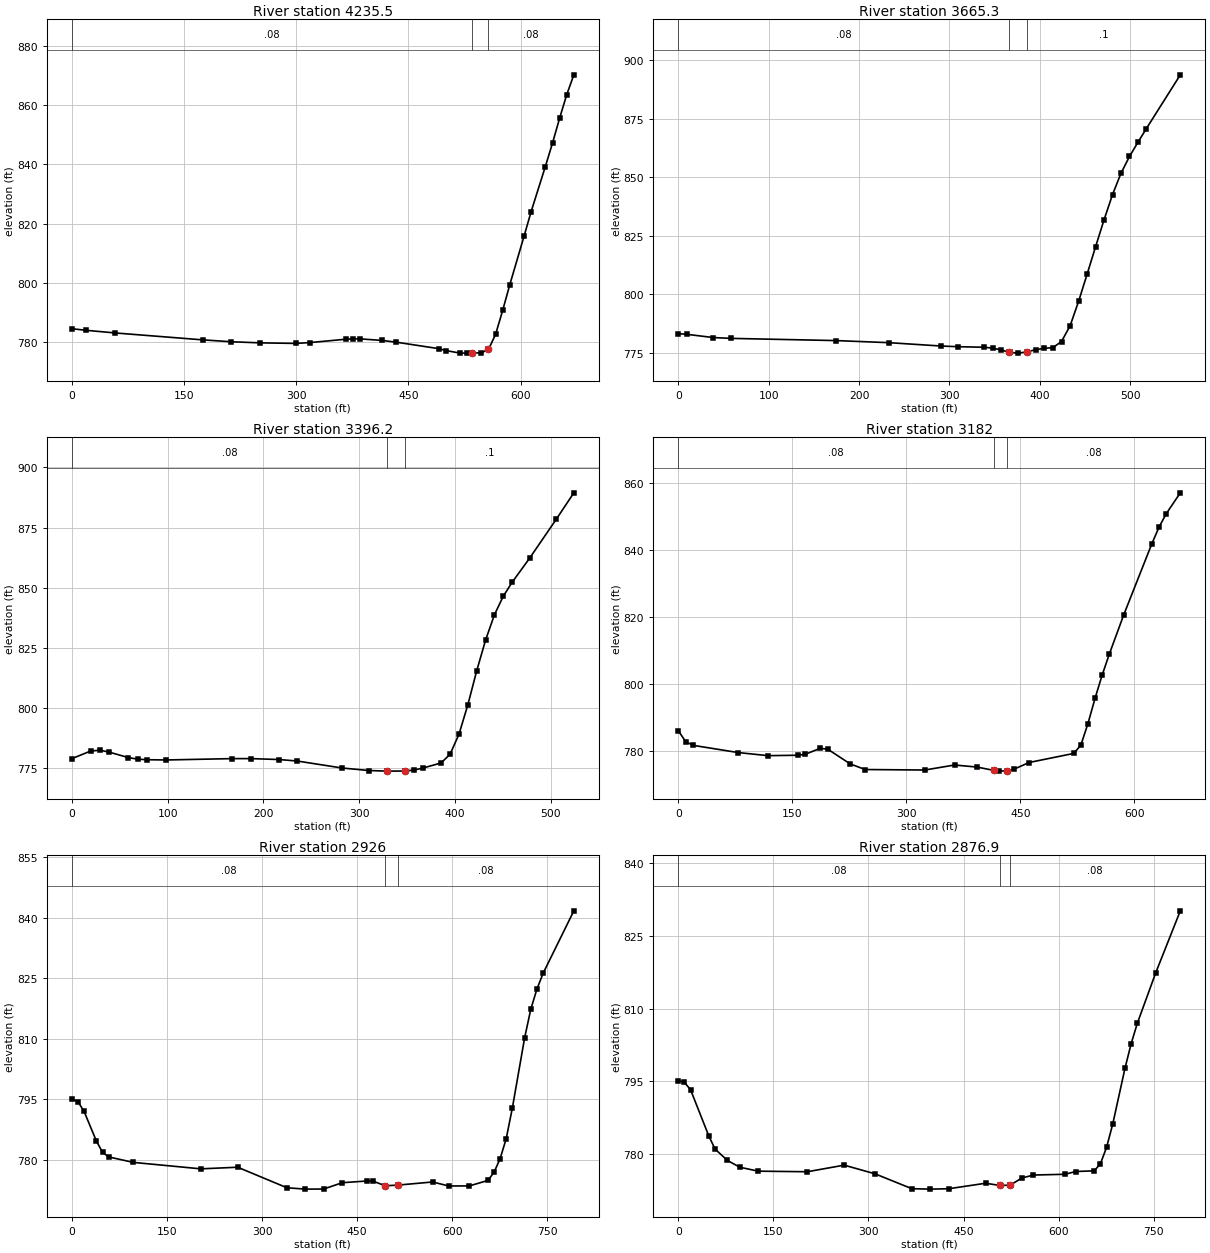
Type RM Length L Ch R = 1 ,4235.5  ,539.6,570.3,568.4
XS GIS Cut Line= 4
      1675681.82       683713.31     1675832.862      683819.212
     1676004.737       683971.99      1676181.82      684157.754
#Sta/Elev= 30
       0  784.64    19.4   784.1    58.2  783.21   174.8  780.89   213.2  780.25
   251.5  779.88   299.4  779.69   318.6  779.98   366.5   781.1   376.1  781.25
   385.7  781.21   414.4   780.7   433.4  780.12   490.5  777.93     500  777.29
     519  776.43   528.5  776.42   534.6  776.44   547.5  776.55     557  777.66
   566.5  782.74     576  790.85   585.5  799.47   604.5  815.76     614  824.07
     633  839.25   642.6  847.17   652.1  855.54   661.6  863.46   671.1  870.13
#Mann= 3 , 0 , 0
       0     .08       0   534.6    .045       0     557     .08       0
Bank Sta=534.6,557
XS Rating Curve= 0 ,0
Exp/Cntr=0.3,0.1

Type RM Length L Ch R = 1 ,3665.3  ,261.2,269,271.1
XS GIS Cut Line= 4
     1675412.723      683945.949     1675544.668      684161.226
     1675654.043      684305.324     1675711.334      684412.962
#Sta/Elev= 30
       0  783.19     9.7  782.88    38.8  781.51    58.3  781.16   174.8  780.21
   233.1  779.32   290.6  777.89   309.6   777.6   338.2  777.36   347.7     777
   357.2  776.21   365.6  775.27   366.8  775.14   376.3  774.85   385.8   775.4
   395.3  776.31   404.8   776.9   414.4   777.2   423.9  779.82   433.4  786.53
   442.8  796.99   452.2   808.6   461.5  820.24   470.9  831.81   480.3  842.63
   489.7  851.79   499.1  858.96   508.4  865.02   517.8   870.9   555.3  893.87
#Mann= 3 , 0 , 0
       0     .08       0   365.6    .045       0   385.8      .1       0
Bank Sta=365.6,385.8
XS Rating Curve= 0 ,0
Exp/Cntr=0.3,0.1

Type RM Length L Ch R = 1 ,3396.2  ,216.6,214.2,206
XS GIS Cut Line= 4
     1675253.001      684086.574     1675381.473      684272.337
     1675473.487      684425.115      1675548.14      684518.865
#Sta/Elev= 30
       0  779.07    19.6  782.23    29.5  782.59    39.3  781.76    58.9  779.54
    68.7  778.87    78.6  778.64    98.2  778.53   166.9  779.09   186.6   779.1
     216  778.72   235.2   778.1   282.2  775.19   310.3  774.15   329.1   773.9
   347.9  773.95   357.3  774.36   366.7   775.2   385.4  777.29   394.8  780.89
   404.2  789.31   413.4  801.49   422.6  815.53   431.9  828.36   441.1  838.81
   450.3  846.49   459.5  852.26     478  862.42   505.6  878.47     524  889.47
#Mann= 3 , 0 , 0
       0     .08       0   329.1    .045       0   347.9      .1       0
Bank Sta=329.1,347.9
XS Rating Curve= 0 ,0
Exp/Cntr=0.3,0.1

Type RM Length L Ch R = 1 ,3182    ,252.4,256,250.2
XS GIS Cut Line= 4
     1674971.751      684145.601     1675133.209      684289.699
     1675332.862      684518.865     1675426.612      684623.032
#Sta/Elev= 30
       0  785.99     9.8  782.66    19.7  781.56    78.7  779.41     118  778.48
   157.4   778.6   167.2  778.91   186.9  780.68   196.7  780.41   226.2  776.02
   245.8  774.33   324.3  774.18   363.5  775.68   392.9  775.07   415.5  774.06
   422.3  773.85   432.1  773.95   441.9  774.44   461.5  776.43   520.4  779.15
   529.7  781.66     539  788.08   548.4   795.7   557.7  802.61   567.1  808.87
   585.8  820.45   623.1  841.91   632.5  846.85   641.8  850.81   660.5  857.12
#Mann= 3 , 0 , 0
       0     .08       0   415.5    .045       0   432.1     .08       0
Bank Sta=415.5,432.1
XS Rating Curve= 0 ,0
Exp/Cntr=0.3,0.1

Type RM Length L Ch R = 1 ,2926    ,48.9,49,50.3
XS GIS Cut Line= 6
     1674749.529      684287.962     1675075.918      684591.782
     1675145.362      684643.865     1675174.876      684689.004
      1675181.82      684718.518     1675308.557       684838.31
#Sta/Elev= 30
       0   795.1     9.7  794.45    19.4  792.04    38.8  784.71    48.5  781.92
    58.2  780.77    96.9  779.42   203.6  777.82   261.7  778.22   339.3  773.14
   368.4   772.8   397.4  772.83   426.5  774.39   465.3  774.81     475  774.78
   494.5  773.63   513.8  773.79   569.1  774.57   594.6  773.57   627.1   773.6
   656.1  774.94   665.8  776.92   675.5  780.33   685.2  785.32   694.9  792.95
   714.2  810.26   723.9  817.32   733.6  822.33   743.3  826.21   791.8  841.68
#Mann= 3 , 0 , 0
       0     .08       0   494.5    .045       0   513.8     .08       0
Bank Sta=494.5,513.8
XS Rating Curve= 0 ,0
Exp/Cntr=0.3,0.1

Type RM Length L Ch R = 1 ,2876.9  ,79.7,79,79.5
XS GIS Cut Line= 6
      1674713.07      684320.949     1675039.459      684624.768
     1675108.904      684676.851     1675138.418       684721.99
     1675145.362      684751.504     1675272.098      684871.296
#Sta/Elev= 30
       0  795.17     9.7  794.82    19.4  793.31    48.5  783.68    58.2  781.06
    77.6  778.74    96.9  777.35     126  776.53   203.6  776.41   261.7  777.77
   310.2  775.99   368.4  772.92   397.4  772.83   426.5  772.91   484.7  774.04
   507.1  773.59   523.4  773.64   542.1  775.13   560.1  775.73   609.8  775.89
   627.1  776.46   656.1   776.6   665.8  778.06   675.5  781.43   685.2  786.22
   704.6  797.75   714.2  802.76   723.9  806.95     753  817.38   791.8  830.15
#Mann= 3 , 0 , 0
       0     .08       0   507.1    .045       0   523.4     .08       0
Bank Sta=507.1,523.4
XS Rating Curve= 0 ,0
Exp/Cntr=0.3,0.1