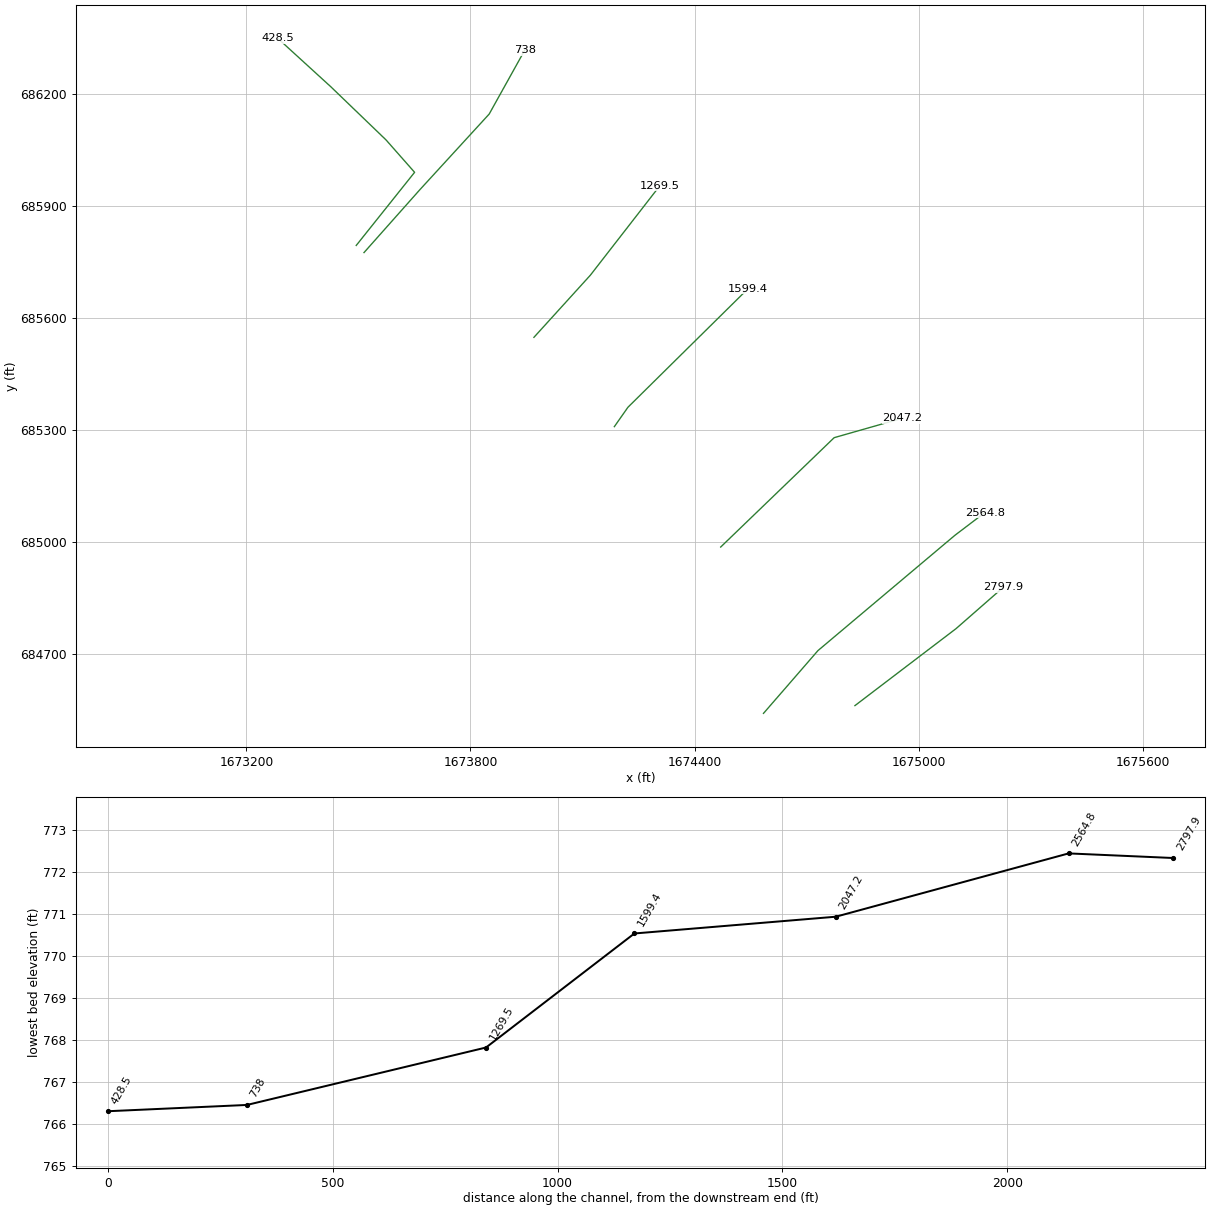
HEC-RAS study ALXNDRSRN.prj: ALXNDRSRN

--- ALXNDRSRN.g01 (geometry) --- (continued)

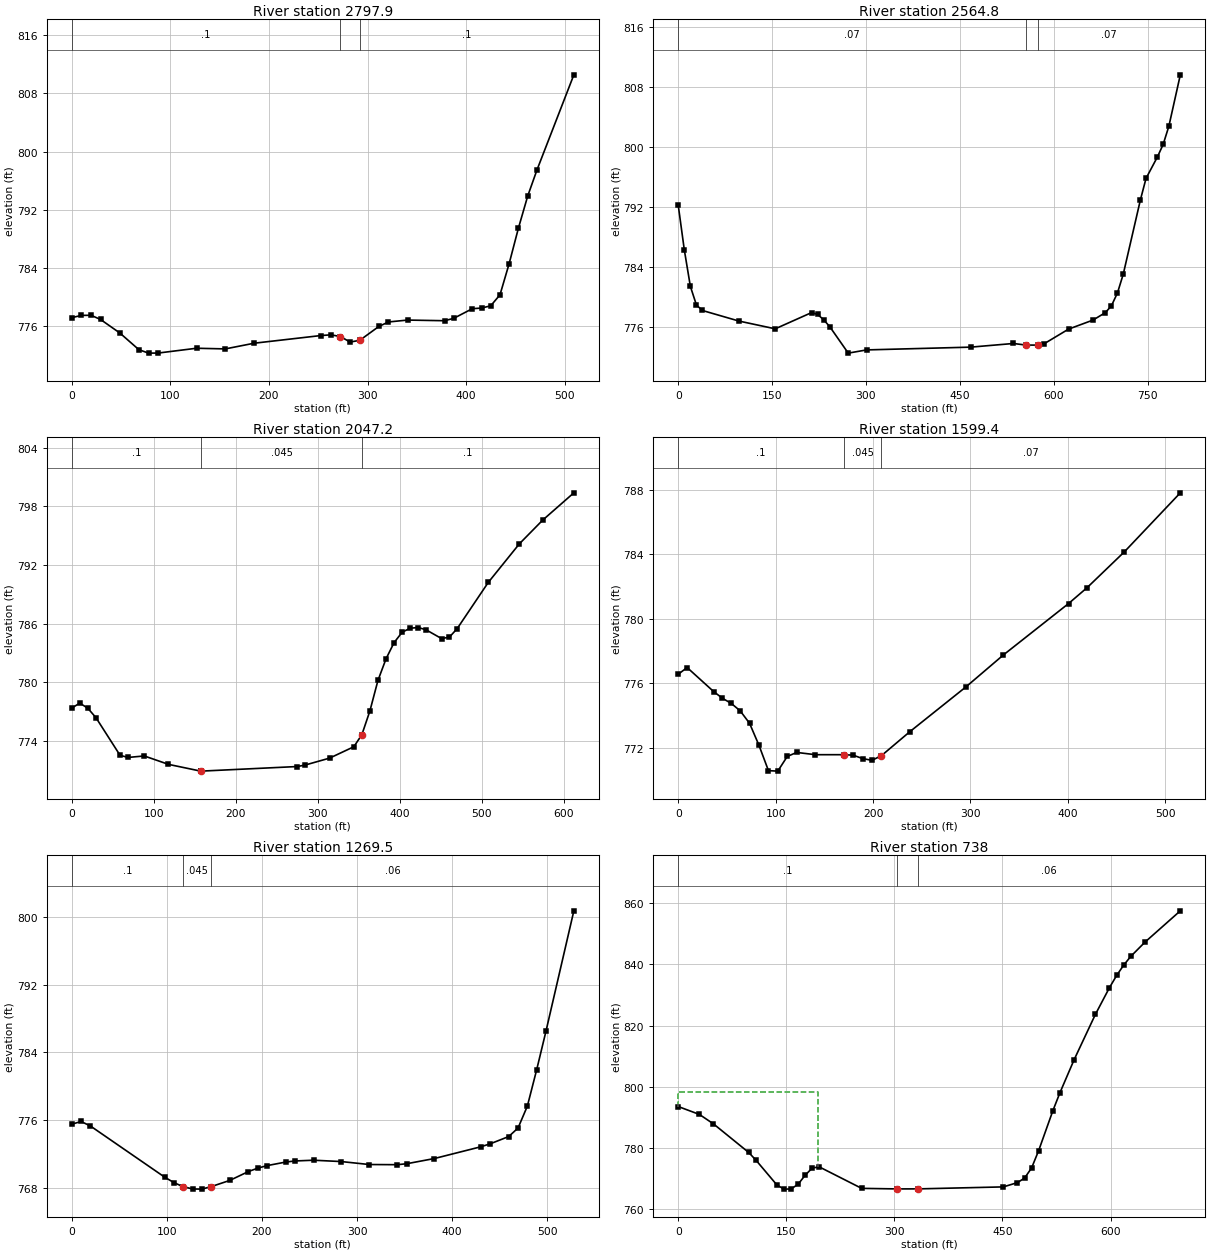
Type RM Length L Ch R = 1 ,2797.9  ,226.6,233.1,229
XS GIS Cut Line= 3
      1674829.39      684560.532     1675100.223      684767.129
     1675226.959       684878.24
#Sta/Elev= 30
       0  777.21     9.7  777.52    19.5  777.54    29.2  776.96    48.7  775.11
    68.1  772.81    77.9  772.34    87.6  772.35   126.5  773.01   155.7  772.92
   184.9   773.7     253  774.76   262.8  774.85   272.5  774.62   282.2  773.86
   292.1   774.1   311.4     776   321.2  776.62   340.6  776.88   378.1  776.79
   387.4  777.12   406.2  778.44   415.6  778.53   424.9  778.84   434.3  780.35
   443.6  784.64     453  789.51   462.4  793.91   471.7  797.46   509.2  810.56
#Mann= 3 , 0 , 0
       0      .1       0   272.5    .045       0   292.1      .1       0
Bank Sta=272.5,292.1
XS Rating Curve= 0 ,0
Exp/Cntr=0.3,0.1

Type RM Length L Ch R = 1 ,2564.8  ,514.4,517.6,519
XS GIS Cut Line= 4
     1674584.598      684539.699     1674730.432      684708.101
     1675096.751      685017.129     1675176.612      685077.893
#Sta/Elev= 30
       0  792.22     9.7  786.26    19.4  781.37    29.1  778.88    38.7  778.15
    96.9  776.74     155   775.7   213.1  777.87   222.8  777.62   232.6   776.9
   242.3  775.97   271.7  772.45     301  772.88   467.3  773.25   535.8  773.74
   555.3  773.53   574.9  773.52   584.7   773.7   623.8  775.66   662.9  776.87
   682.5  777.86   692.2  778.76     702  780.51   711.2     783   738.5   792.9
   747.6  795.81   765.9   798.7     775  800.36   784.1  802.79   802.4  809.66
#Mann= 3 , 0 , 0
       0     .07       0   555.3    .045       0   574.9     .07       0
Bank Sta=555.3,574.9
XS Rating Curve= 0 ,0
Exp/Cntr=0.3,0.1

Type RM Length L Ch R = 1 ,2047.2  ,446.8,447.8,447.4
XS GIS Cut Line= 3
     1674470.015      684985.879     1674773.834      685279.282
     1674956.126      685331.365
#Sta/Elev= 30
       0  777.38     9.8  777.89    19.6  777.36    29.5   776.4    58.9  772.55
    68.8  772.34    88.4  772.49   117.9  771.63   157.2  770.94   157.6  770.94
     275  771.41   284.8  771.57   314.3  772.27   343.8  773.43   353.6  774.66
   363.4  777.09   373.2   780.2   383.1  782.42   392.9  784.07   402.7  785.13
   412.5  785.54   422.4  785.61   431.8  785.38   450.8  784.48   460.3  784.63
   469.8   785.5   507.7  790.22   545.6  794.16     574  796.58     612  799.37
#Mann= 3 , 0 , 0
       0      .1       0   157.6    .045       0   353.6      .1       0
Bank Sta=157.6,353.6
XS Rating Curve= 0 ,0
Exp/Cntr=0.3,0.1

Type RM Length L Ch R = 1 ,1599.4  ,327.3,329.9,330
XS GIS Cut Line= 4
     1674185.293      685308.796     1674221.751      685360.879
     1674386.682      685524.074     1674542.932      685678.587
#Sta/Elev= 25
       0  776.55     9.1  776.97    36.3  775.48    45.4  775.06    54.5  774.74
    63.6  774.28    73.2  773.51    82.9  772.14    92.6  770.57   102.2  770.54
   111.9  771.45   121.6   771.7   140.9  771.56   169.9  771.56   179.6  771.53
   189.2  771.32   198.9  771.21   208.6   771.5   237.6  772.98   295.6  775.78
   333.8  777.75   400.7  780.94   419.8  781.93     458  784.15   515.4  787.81
#Mann= 3 , 0 , 0
       0      .1       0   169.9    .045       0   208.6     .07       0
Bank Sta=169.9,208.6
XS Rating Curve= 0 ,0
Exp/Cntr=0.3,0.1

Type RM Length L Ch R = 1 ,1269.5  ,532.8,531.5,528.8
XS GIS Cut Line= 3
     1673970.015      685548.379     1674121.057      685715.046
      1674306.82      685954.629
#Sta/Elev= 29
       0   775.5     9.8  775.82    19.6  775.29    97.8  769.23   107.6  768.58
   117.2  768.11   127.1  767.84   136.9  767.82   146.7  768.12   166.2  768.85
   185.8   769.9   195.6   770.3   205.4   770.6   224.9  771.02   234.7  771.15
   254.3  771.24   283.6  771.08   312.9  770.73   342.3  770.71   352.1  770.82
   381.4  771.44   430.3  772.83   440.1  773.18   459.6  774.04   469.4  775.05
   479.2  777.64     489  781.94   498.8  786.51   528.1  800.74
#Mann= 3 , 0 , 0
       0      .1       0   117.2    .045       0   146.7     .06       0
Bank Sta=117.2,146.7
XS Rating Curve= 0 ,0
Exp/Cntr=0.3,0.1

Type RM Length L Ch R = 1 ,738     ,269,309.5,345.6
XS GIS Cut Line= 4
     1673515.154       685775.81     1673664.459      685944.212
     1673850.223      686147.337     1673945.709      686319.212
#Sta/Elev= 30
       0  793.49    29.4   790.9    48.9  787.81    97.8  778.45   107.6  776.01
     137   767.8   146.8  766.45   156.6   766.5   166.4  768.05   176.1  770.98
   185.9  773.34   195.7  773.74   254.6   766.7   303.7  766.52   333.2  766.53
   451.2  767.18   470.8  768.58   480.7  770.06   490.5  773.39   500.3  779.08
     520  792.12   529.8     798   549.5  808.82     579  823.64   598.6  832.43
   608.5  836.39   618.3  839.78   628.1  842.63   647.8   847.3   696.9  857.56
#Mann= 3 , 0 , 0
       0      .1       0   303.7    .045       0   333.2     .06       0
#XS Ineff= 2 , 0
          194.07  798.14
Permanent Ineff=
       F       F
Bank Sta=303.7,333.2
XS Rating Curve= 0 ,0
Exp/Cntr=0.3,0.1

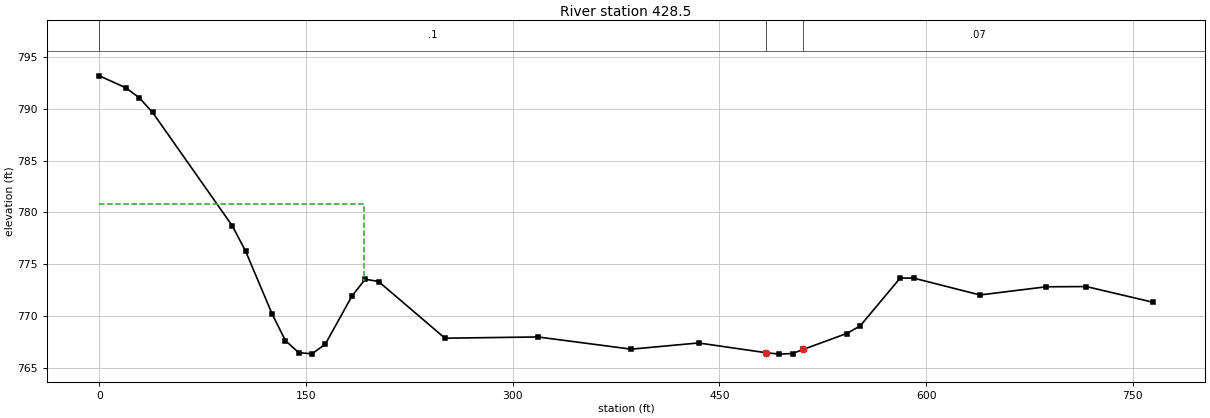
Type RM Length L Ch R = 1 ,428.5   ,468.6,428.5,389.4
XS GIS Cut Line= 5
      1673494.32      685794.907      1673650.57      685991.087
     1673574.182      686077.893     1673426.612      686220.254
     1673284.251      686350.462
#Sta/Elev= 30
       0   793.2    19.3  792.04    28.9  791.09    38.6  789.67    96.5   778.7
   106.1  776.26   125.4  770.18     135  767.61   144.7  766.44   154.3  766.33
     164  767.27   183.3  771.91   192.9  773.54   202.6  773.32   250.8  767.84
   318.2  767.96     386  766.78   434.8  767.38   483.6  766.44   493.4   766.3
   503.1  766.36   510.7  766.75   542.2  768.29     552  769.01   581.1  773.65
   590.8  773.65     639  772.02   687.2  772.81   716.2  772.83   764.4  771.32
#Mann= 3 , 0 , 0
       0      .1       0   483.6    .045       0   510.7     .07       0
#XS Ineff= 2 , 0
          192.03   780.8
Permanent Ineff=
       F       F
Bank Sta=483.6,510.7
XS Rating Curve= 0 ,0
Exp/Cntr=0.3,0.1

Chan Stop Cuts=-1
Use User Specified Reach Order=0
Composite Channel Slope=5